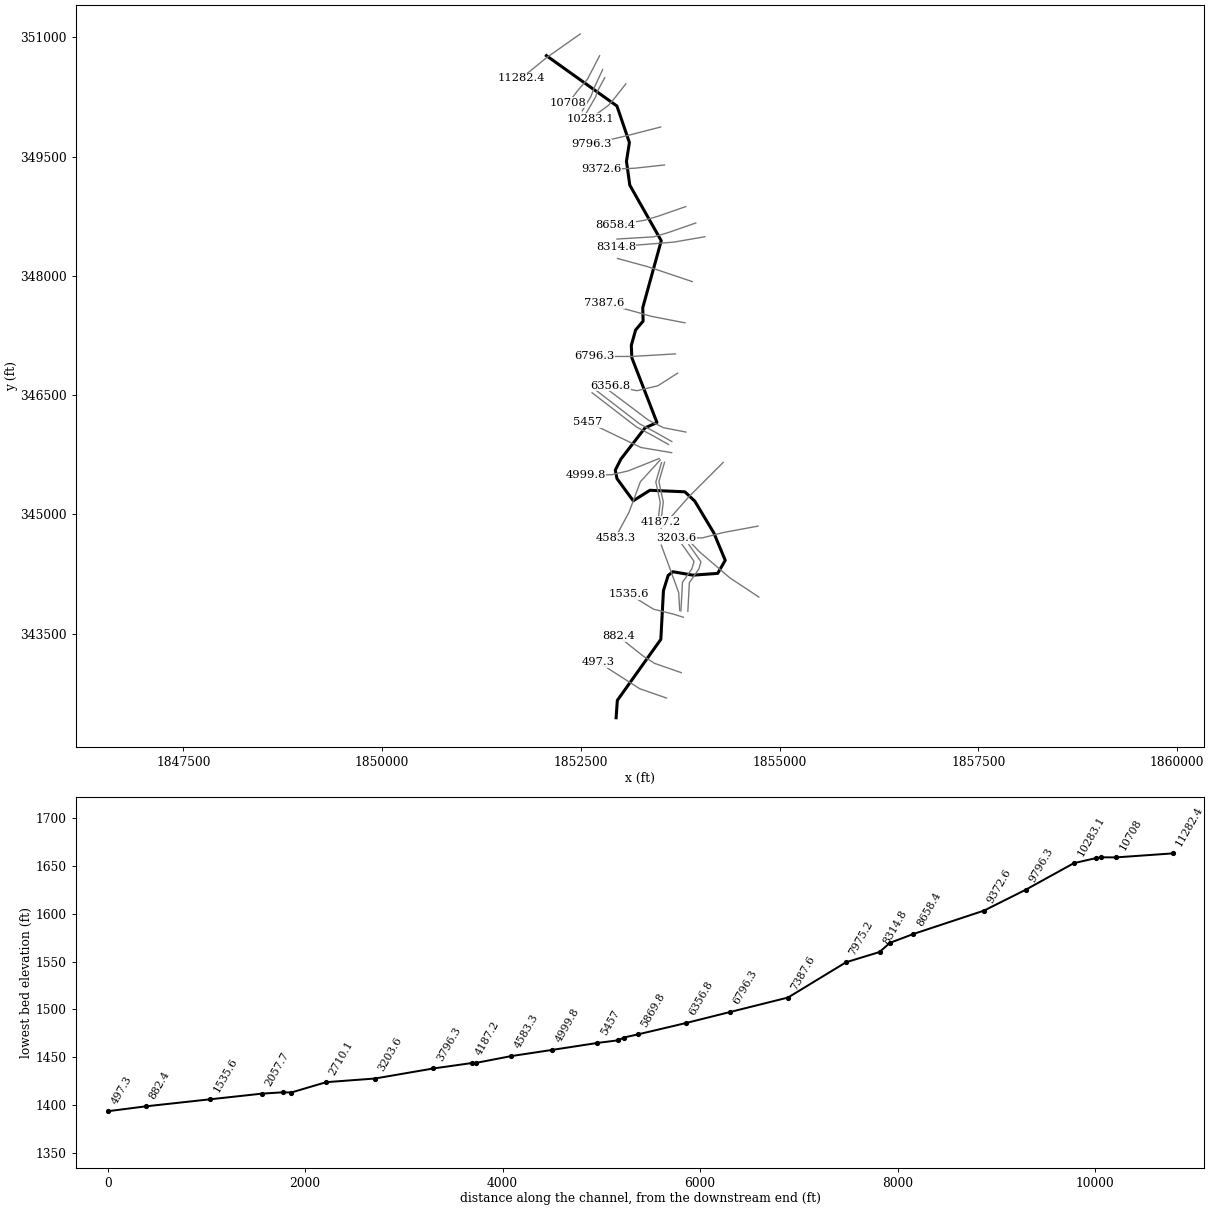
--- LaurelRun.prj (project) ---

Proj Title=LaurelRun
Current Plan=p01
Default Exp/Contr=0,0
English Units
Geom File=g01
Flow File=f01
Plan File=p01
BEGIN DESCRIPTION:
END DESCRIPTION:
DSS Export Rating Curves= 0
DSS Export Rating Curve Sorted= 0
DSS Export Volume Flow Curves= 0
DXF OffsetX= 0
DXF OffsetY= 0
DXF ScaleX= 0
DXF ScaleY= 0

--- LaurelRun.p01 (plan) ---

Plan Title=Floodplain
Program Version=4.00
Geom File=g01
Flow File=f01
K Sum by GR=0
Std Step Tol=0.01
Critical Tol=0.01
Num of Std Step Trials=20
Max Error Tol=0.3
Flow Tol Ratio=0.001
Split Flow NTrial=30
Split Flow Tol=0.02
Split Flow Ratio=0.02
Log Output Level=0
Friction Slope Method=1
Unsteady Friction Slope Method=2
Unsteady Bridges Friction Slope Method=1
Global Log Level=0
CheckData=False
Run HTab=0
Run UNet=0
Run PostProcess=0
UNET Theta=0
UNET Theta Warmup=0
UNET ZTol=0
UNET ZSATol=0
UNET MxIter=0
UNET MaxInSteps=0
UNET DtIC=0
UNET DtMin=0
UNET MaxCRTS=0
UNET WFStab=0
UNET SFStab=0
UNET WFX=0
UNET SFX=0
UNET DSS MLevel=0
UNET DZMax Abort=0
UNET Convert EG Bridges=0
UNET Use Existing IB Tables=0
UNET Froude Limit=0
UNET Froude Power=0
Write IC File=0
Echo Input=False
Echo Output=False
Write Detailed=0

--- LaurelRun.f01 (steady flow) ---

Flow Title=NFF Regression Equation
Program Version=4.10
Number of Profiles= 1
Profile Names=P100yr
River Rch & RM=LaurelRun,Main            ,11282.4
     819
River Rch & RM=LaurelRun,Main            ,8314.8
     844
River Rch & RM=LaurelRun,Main            ,7975.2
    1006
River Rch & RM=LaurelRun,Main            ,5869.8
    1104
River Rch & RM=LaurelRun,Main            ,4999.8
    1341
River Rch & RM=LaurelRun,Main            ,2356.1
    1421
River Rch & RM=LaurelRun,Main            ,497.3
    1487
Boundary for River Rch & Prof#=LaurelRun,Main            , 1
Up Type= 0
Dn Type= 3
Dn Slope=0.01275
DSS Import GetInterval= 0
DSS Import GetPeak= 0
DSS Import FillOption= 0

--- LaurelRun.g01 (geometry) ---

Geom Title=USGS 10m DEM
Program Version=4.10

River Reach=LaurelRun       ,Main
Reach XY= 30
     1852066.319       350771.47     1852953.472       350137.79
     1853110.274      349678.292     1853073.264      349443.345
      1853114.93      349142.998     1853510.764      348443.345
     1853278.125      347601.331     1853282.525      347432.363
     1853188.289      347320.402     1853134.028      347127.373
     1853140.972      346971.123     1853456.944      346156.887
     1853306.258      346088.845     1853004.219        345698.6
     1852932.638      345557.929     1852953.472      345452.026
     1853158.333      345172.512     1853367.658      345304.456
     1853807.639      345285.359     1853932.812      345167.912
     1854172.222      344767.998     1854315.685      344423.565
     1854220.833      344259.318     1853910.069      344236.748
     1853656.101      344280.151     1853597.569      344233.276
     1853538.541      344042.304     1853505.555      343429.456
     1852958.547      342662.111     1852942.963       342443.37

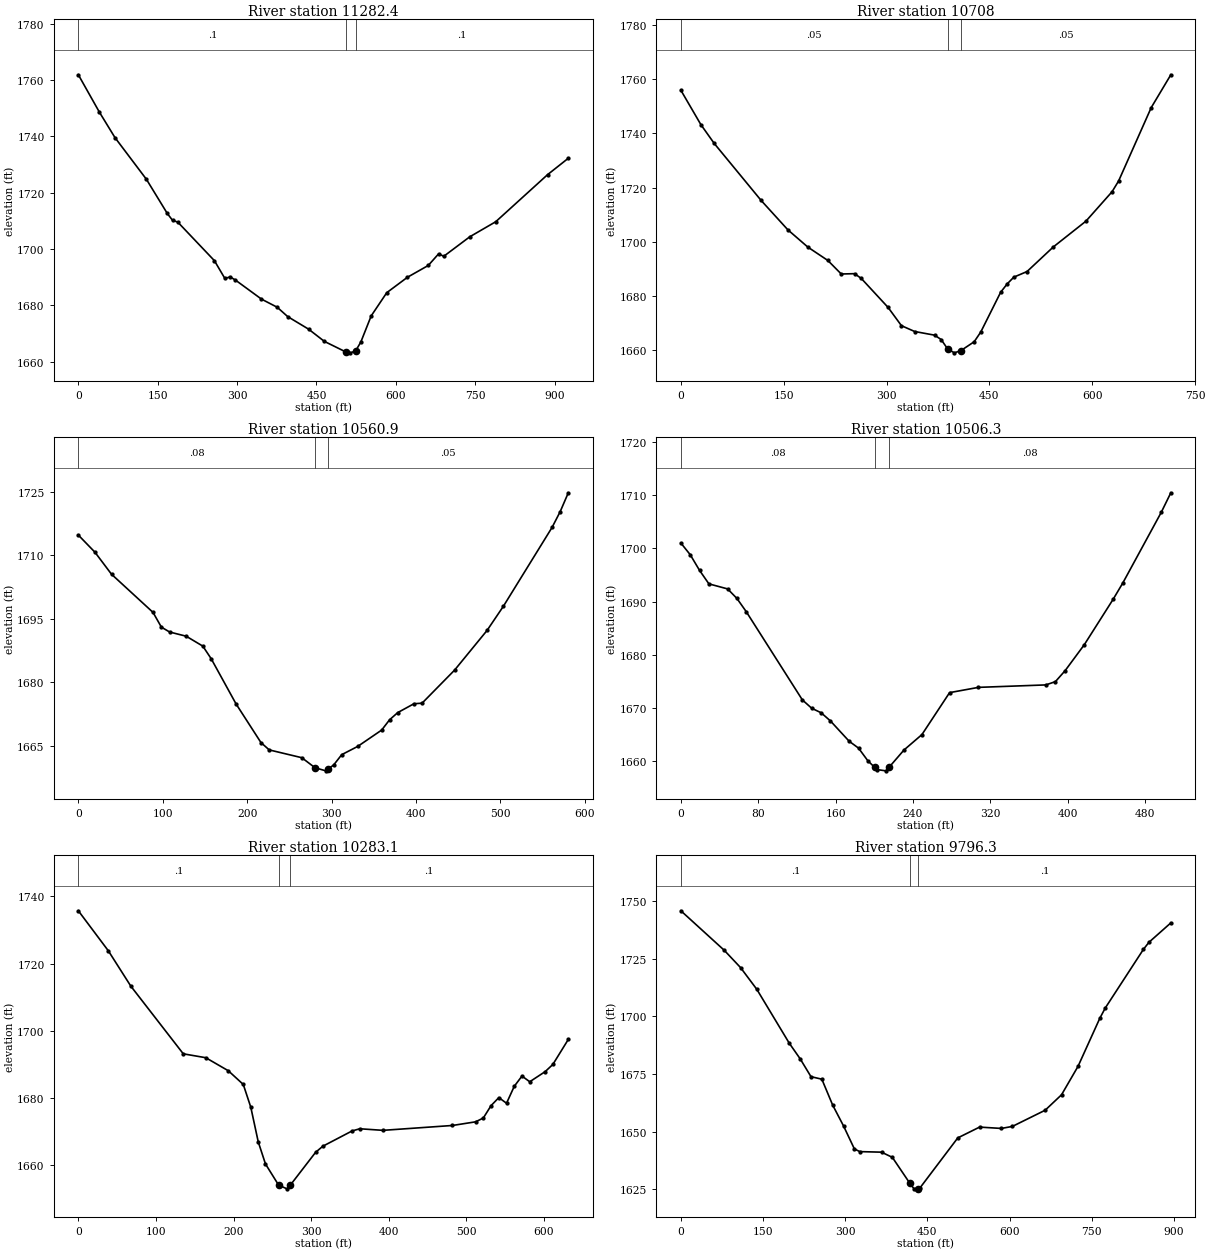
Type RM Length L Ch R = 1 ,11282.4 ,568.6,574.5,578.2
XS GIS Cut Line= 3
     1852491.963      351044.256     1852071.368      350748.418
     1851751.945        350488.7
#Sta/Elev= 30
       0 1761.86    39.6 1748.64    69.2 1739.55   128.6 1724.75   168.1  1712.6
     178 1710.18   187.9 1709.54   257.1 1695.85   276.9 1689.53   286.8 1690.08
   296.7 1688.98   346.1 1682.19   375.8 1679.31   395.6 1675.99   435.1 1671.53
   464.8  1667.2   506.7 1663.32   514.2 1663.12     524 1663.82   533.8 1666.95
   553.4 1676.24   582.8 1684.48     622 1689.97   661.2 1694.14   680.8 1698.27
   690.6 1697.41   739.7 1704.33   788.7 1709.67   886.7 1726.39   925.9 1732.22
#Mann= 3 , 0 , 0
       0      .1       0   506.7    .045       0     524      .1       0
Bank Sta=506.7,524
XS Rating Curve= 0 ,0
Exp/Cntr=0.3,0.1

Type RM Length L Ch R = 1 ,10708   ,139.1,147.1,155
XS GIS Cut Line= 4
     1852735.344      350770.059     1852583.109       350475.68
     1852463.751      350336.791     1852342.549      350177.611
#Sta/Elev= 30
       0 1755.92    29.2 1743.22    48.7 1736.26     117 1715.24     156 1704.39
   185.2 1697.99   214.4 1693.05   233.9 1688.06   253.4 1688.18   263.2  1686.4
   302.2 1675.72   321.7 1668.97     341 1666.82     370 1665.47   379.6 1663.86
   389.2 1660.34   398.9 1658.94   408.5 1659.78   427.8 1663.04   437.4 1666.63
   466.4 1681.32     476 1684.42   485.6  1686.9   504.9 1688.97   543.1 1698.03
   590.8 1707.58   628.9 1718.45   638.4  1722.4     686 1749.52   714.6 1761.64
#Mann= 3 , 0 , 0
       0     .05       0   389.2    .045       0   408.5     .05       0
Bank Sta=389.2,408.5
XS Rating Curve= 0 ,0
Exp/Cntr=0.3,0.1

Type RM Length L Ch R = 1 ,10560.9 ,55,54.6,55.7
XS GIS Cut Line= 4
     1852773.972      350596.448     1852669.914      350373.683
     1852626.511      350258.666     1852517.028      350077.351
#Sta/Elev= 30
       0 1714.71    19.7 1710.66    39.3 1705.47    88.5 1696.46    98.4 1692.98
   108.2 1691.83   127.8 1690.84   147.5  1688.5   157.4 1685.53   186.9 1674.85
   216.4 1665.73   226.2    1664   264.8 1662.16   280.4  1659.8   293.2 1659.06
   295.4 1659.39   302.6 1660.46   312.1 1662.88     331 1664.82   359.4 1668.68
   368.8 1671.11   378.4  1672.8   397.7  1674.9   407.3 1675.03   445.8 1682.83
   484.3  1692.2   503.6 1697.89   561.4 1716.54     571 1720.26   580.6  1724.7
#Mann= 3 , 0 , 0
       0     .08       0   280.4    .045       0   295.4     .05       0
Bank Sta=280.4,295.4
XS Rating Curve= 0 ,0
Exp/Cntr=0.3,0.1

Type RM Length L Ch R = 1 ,10506.3 ,230.5,223.3,214.4
XS GIS Cut Line= 4
     1852800.014      350494.017        1852708.      350323.878
     1852685.431      350252.698     1852565.639      350046.101
#Sta/Elev= 30
       0 1700.99     9.7 1698.79    19.3 1695.86      29 1693.32    48.4 1692.37
      58 1690.58    67.7 1688.08   125.7 1671.52   135.4 1669.95   145.1 1669.11
   154.7 1667.58   174.1 1663.76   183.8 1662.47   193.4  1660.1   200.5 1658.85
   202.8 1658.44   212.1  1658.2   215.5 1658.89   230.8 1662.11   249.4 1665.01
     278 1672.89   307.9 1673.88   377.6 1674.34   387.5 1674.96   397.5 1677.01
   417.4  1681.9   447.2 1690.42   457.2 1693.48     497 1706.76   506.9 1710.43
#Mann= 3 , 0 , 0
       0     .08       0   200.5    .045       0   215.5     .08       0
Bank Sta=200.5,215.5
XS Rating Curve= 0 ,0
Exp/Cntr=0.3,0.1

Type RM Length L Ch R = 1 ,10283.1 ,500.3,486.8,472.1
XS GIS Cut Line= 4
     1853065.205      350416.326     1852921.976      350234.035
     1852850.361      350149.399     1852618.156      349977.958
#Sta/Elev= 30
       0 1735.73    38.6 1723.82    67.6 1713.29   135.2 1693.13   164.2 1691.97
   193.2 1688.09   212.5 1684.01   222.2 1677.22   231.8  1666.9   241.1 1660.33
     258 1654.05   268.8 1652.92     273 1653.99   305.7  1663.8     315 1665.61
   352.6 1670.15   362.6 1670.81   392.5 1670.34     482 1671.79   511.9 1672.88
   521.8 1674.02   531.8 1677.71   541.8 1680.09   551.7 1678.41   561.7 1683.47
   571.6 1686.51   581.6 1684.81   601.5 1687.83   611.4 1689.97   631.3 1697.42
#Mann= 3 , 0 , 0
       0      .1       0     258    .045       0     273      .1       0
Bank Sta=258,273
XS Rating Curve= 0 ,0
Exp/Cntr=0.3,0.1

Type RM Length L Ch R = 1 ,9796.3  ,428.2,423.7,419.1
XS GIS Cut Line= 3
     1853503.573      349873.792     1853091.387      349767.872
     1852635.517      349658.948
#Sta/Elev= 30
       0 1745.75    79.2 1728.61   108.9 1721.13   138.6  1711.7   197.9 1688.31
   217.7 1681.58   237.5 1673.82   257.3 1672.73   277.1 1661.49   296.9 1652.46
   316.7 1642.49   326.6 1641.33   366.2 1641.09     386 1638.84   418.1 1627.54
   425.6 1625.19   433.1  1625.3   435.6 1625.34   505.4 1647.27   545.2 1651.96
   585.1 1651.38   605.1 1652.26   664.9 1659.27   694.8 1665.97   724.8 1678.25
   764.6  1699.1   774.6 1703.59   844.4 1729.07   854.4  1732.1   894.3  1740.5
#Mann= 3 , 0 , 0
       0      .1       0   418.1    .045       0   433.1      .1       0
Bank Sta=418.1,433.1
XS Rating Curve= 0 ,0
Exp/Cntr=0.3,0.1

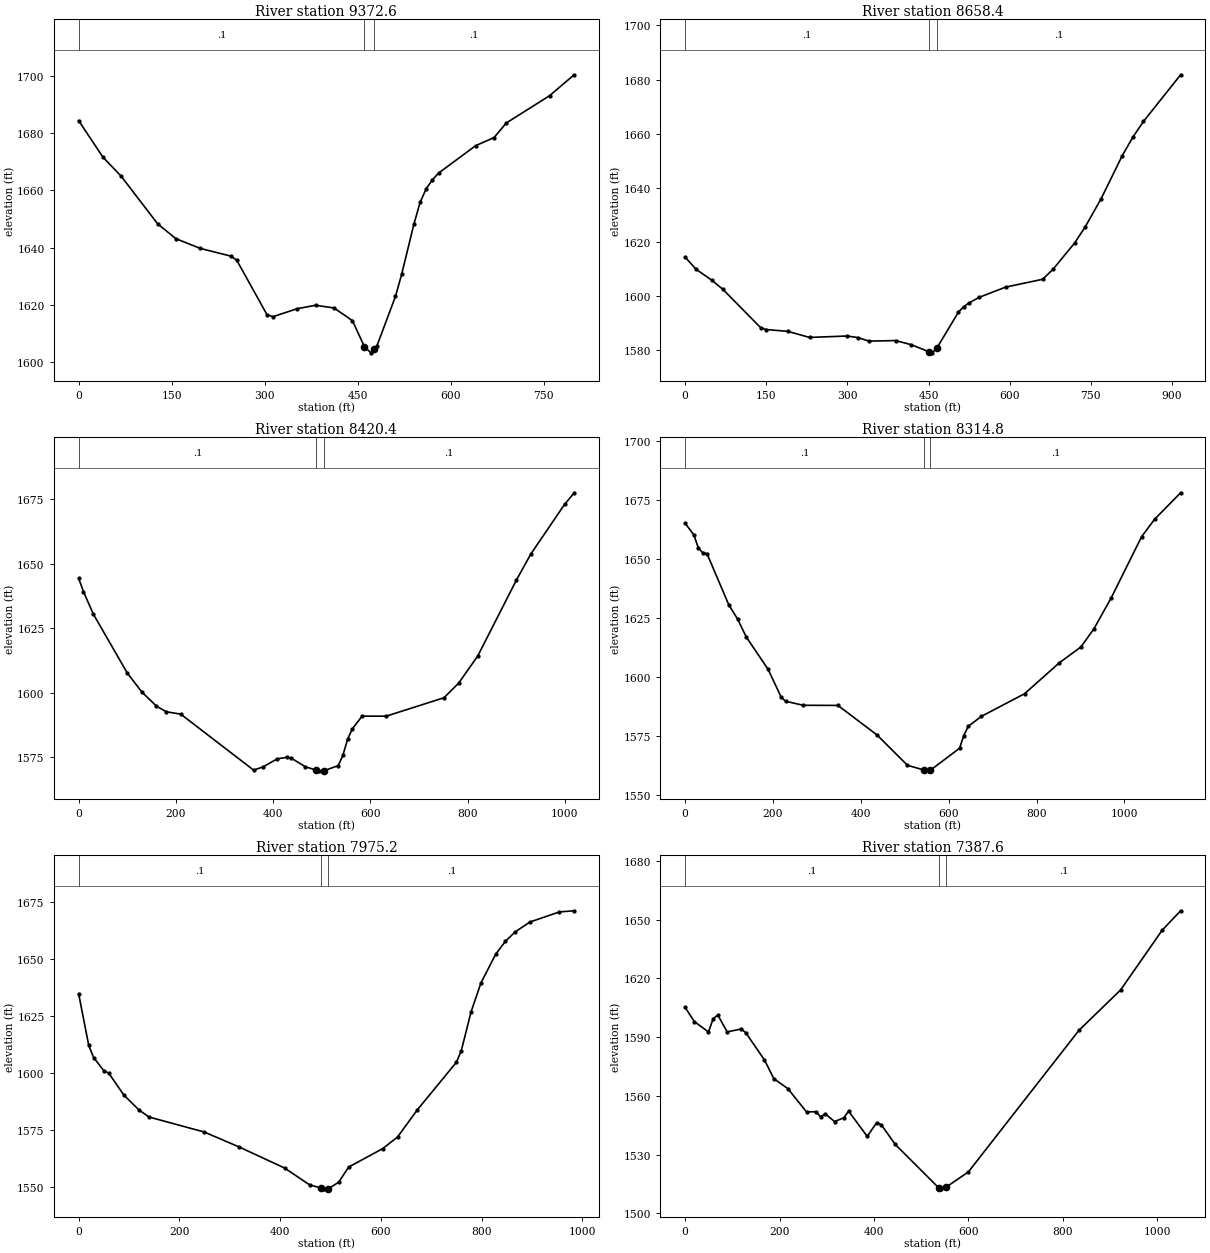
Type RM Length L Ch R = 1 ,9372.6  ,708.2,714.2,719.4
XS GIS Cut Line= 4
     1853551.316      349396.361     1853171.542      349355.128
     1853013.122      349348.618     1852754.875      349342.108
#Sta/Elev= 30
       0  1684.4    39.2 1671.63    68.6 1664.97   127.3 1648.38   156.7 1643.18
   195.9 1639.79   244.9 1637.11   254.7 1635.74   303.6 1616.67   313.4 1615.94
   352.6 1618.75     382 1619.92   411.7 1618.99   441.5 1614.54   460.8 1605.43
   471.2 1603.32   475.8  1604.5   481.1 1605.87   510.8 1623.02   520.7 1630.67
   540.6 1648.31   550.5 1655.84   560.4 1660.63   570.4 1663.73   580.3 1666.07
   639.9 1675.62   669.7 1678.47   689.6 1683.58   759.2 1693.08   798.9 1700.39
#Mann= 3 , 0 , 0
       0      .1       0   460.8    .045       0   475.8      .1       0
Bank Sta=460.8,475.8
XS Rating Curve= 0 ,0
Exp/Cntr=0.3,0.1

Type RM Length L Ch R = 1 ,8658.4  ,238.1,238.1,237.7
XS GIS Cut Line= 4
     1853819.473      348873.068     1853470.081       348751.54
     1853294.299      348699.457     1852936.226      348640.863
#Sta/Elev= 30
       0 1614.35      20 1609.89      50  1605.7      70 1602.39     140 1588.18
     150 1587.55     190 1586.89     230 1584.63   299.9 1585.17   319.9 1584.56
   339.9 1583.28   389.2 1583.48   418.2 1581.94   450.5 1579.37   456.8 1578.94
   465.5 1580.72     505  1593.9   514.7 1595.94   524.3 1597.32   543.6 1599.46
   592.5 1603.24   661.1 1606.15   680.7 1609.97     720 1619.53   739.6 1625.47
     769  1635.9   808.2 1651.88   827.8  1658.7   847.4 1664.52   916.1 1681.76
#Mann= 3 , 0 , 0
       0      .1       0   450.5    .045       0   465.5      .1       0
Bank Sta=450.5,465.5
XS Rating Curve= 0 ,0
Exp/Cntr=0.3,0.1

Type RM Length L Ch R = 1 ,8420.4  ,110.2,105.6,101.3
XS GIS Cut Line= 4
     1853944.473      348666.471     1853595.081      348544.943
     1853419.299       348492.86     1852954.239      348464.648
#Sta/Elev= 30
       0 1644.32      10 1639.19      30 1630.55     100 1607.62     130 1600.24
     160 1594.77     180 1592.58     210 1591.65   359.9 1569.94   379.6 1571.19
   408.5 1574.31   427.8 1574.89   437.5 1574.56   466.4 1571.23   488.6 1569.93
   495.4 1569.65     505 1569.72     534 1571.68   543.6 1575.72   553.3    1582
   563.2    1586     583 1590.87   632.6 1590.86   751.5 1598.02   781.3  1603.6
   820.9 1614.23   900.2  1643.6     930 1653.77   999.4 1673.01  1019.2 1677.54
#Mann= 3 , 0 , 0
       0      .1       0   488.6    .045       0     505      .1       0
#XS Ineff= 2 , 0
           426.4 1574.79
Permanent Ineff=
       F       F
Bank Sta=488.6,505
XS Rating Curve= 0 ,0
Exp/Cntr=0.3,0.1

Type RM Length L Ch R = 1 ,8314.8  ,348.3,339.6,330.5
XS GIS Cut Line= 3
     1854059.129      348493.583     1853667.336      348425.933
     1852939.337      348367.715
#Sta/Elev= 30
       0 1665.13    19.9 1660.24    29.8 1654.82    39.8 1652.65    49.7 1652.28
    99.4 1630.54   119.3 1624.54   139.2 1616.88   188.9 1603.15   218.7 1591.34
   228.6 1589.61   268.4 1587.89   347.9 1587.82   437.1 1575.25   506.2  1562.4
   543.3 1560.43   555.5 1560.06   558.3 1560.33   624.6 1569.63   634.4 1575.01
   644.3 1578.92   673.9 1583.13   772.6 1592.78   851.6 1605.89   900.9 1612.64
   930.5 1620.34     970 1633.52  1039.1 1659.45  1068.7 1666.86  1127.9 1678.08
#Mann= 3 , 0 , 0
       0      .1       0   543.3    .045       0   558.3      .1       0
Bank Sta=543.3,558.3
XS Rating Curve= 0 ,0
Exp/Cntr=0.3,0.1

Type RM Length L Ch R = 1 ,7975.2  ,587.1,587.6,587.8
XS GIS Cut Line= 4
     1853900.708      347929.347     1853475.361      348072.576
     1853327.792      348120.319     1852961.038      348220.146
#Sta/Elev= 30
       0 1634.95      20 1612.34    29.9 1606.87    49.9 1601.21    59.8 1600.08
    89.8 1590.49   119.7 1583.97   139.6 1580.86   249.3 1574.28   319.2 1567.66
   408.9 1558.48   458.5 1551.11   481.1 1549.72   487.6 1549.34   496.1 1549.37
   516.7 1552.33   536.1 1558.87   603.9    1567   633.2 1572.06   672.1 1583.87
   750.1 1604.87   759.8  1609.9   779.3 1627.03   798.8 1639.61   828.1 1652.26
   847.6 1657.97   867.1 1662.11   896.3 1666.41   954.8 1670.84     984 1671.33
#Mann= 3 , 0 , 0
       0      .1       0   481.1    .045       0   496.1      .1       0
Bank Sta=481.1,496.1
XS Rating Curve= 0 ,0
Exp/Cntr=0.3,0.1

Type RM Length L Ch R = 1 ,7387.6  ,582.4,591.3,597.2
XS GIS Cut Line= 4
     1853809.563      347410.684     1853382.045      347493.149
     1853186.733      347549.573     1852789.597       347655.91
#Sta/Elev= 30
       0 1605.11    19.8 1597.83    49.5 1592.58    59.4 1599.28    69.3 1601.26
    89.1 1592.59   118.7  1594.1   128.6  1592.2   168.2 1578.26     188 1568.72
   217.7 1563.65   257.3 1551.73   277.1 1551.87     287 1549.25   296.9 1550.78
   316.6 1546.83   336.4 1548.76   346.3 1552.16   385.9 1539.23   405.7 1546.25
   415.6 1545.21   445.1 1535.18   537.9 1512.84   541.9 1512.47   552.9 1513.34
     600 1521.08   834.5 1593.44   922.6 1614.02  1010.7 1644.55  1049.8 1654.46
#Mann= 3 , 0 , 0
       0      .1       0   537.9    .045       0   552.9      .1       0
Bank Sta=537.9,552.9
XS Rating Curve= 0 ,0
Exp/Cntr=0.3,0.1

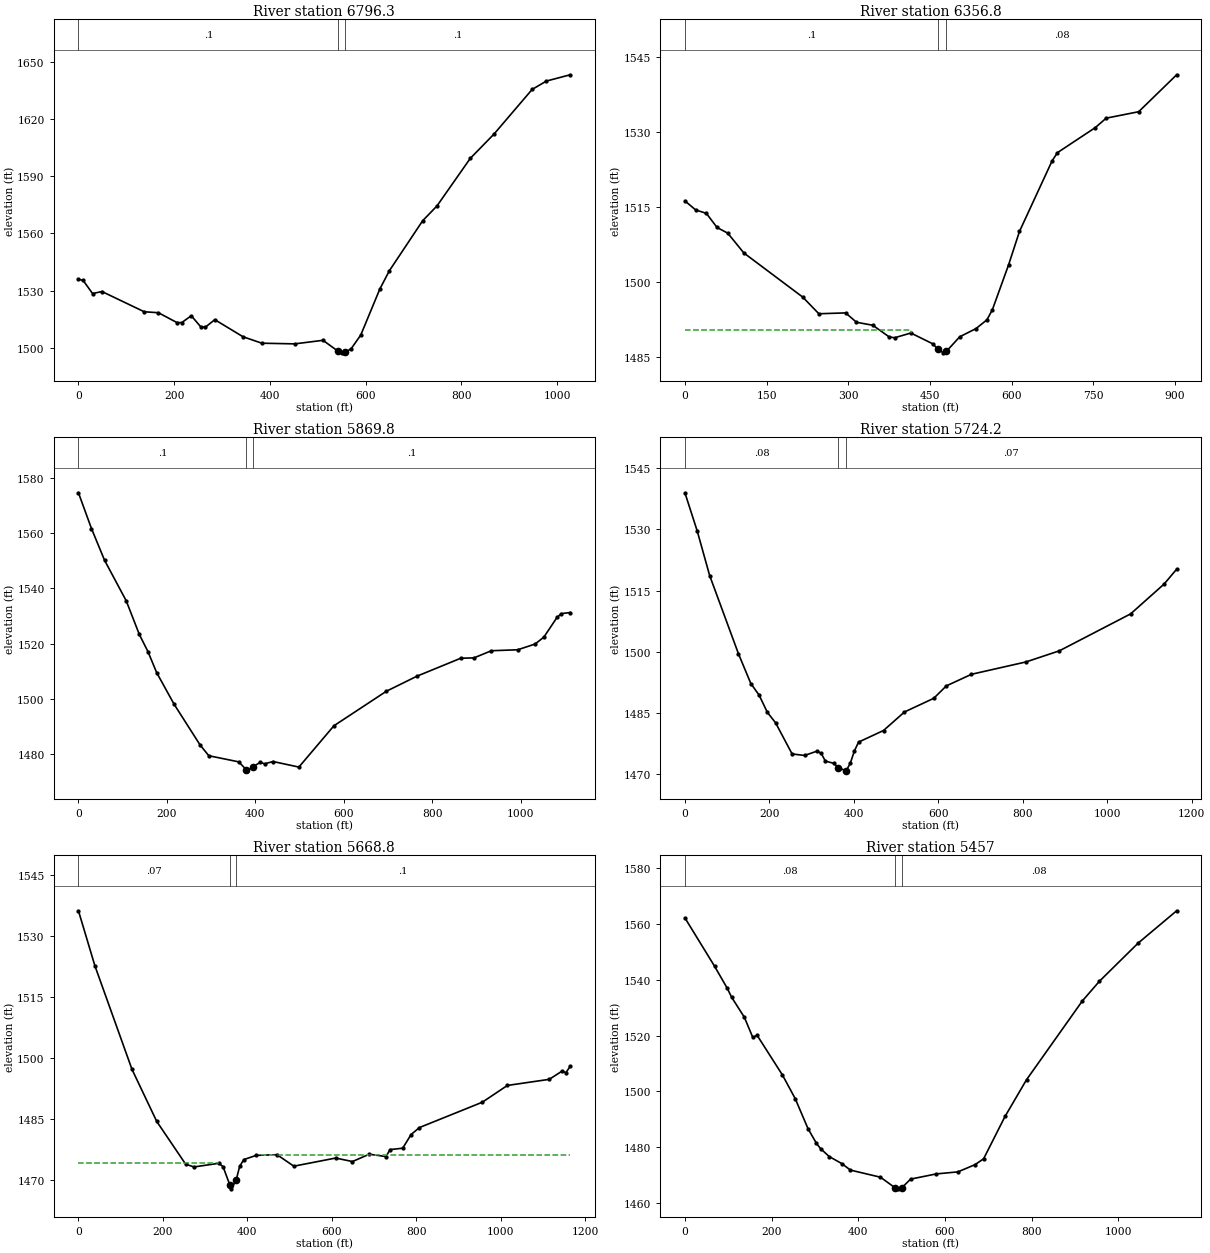
Type RM Length L Ch R = 1 ,6796.3  ,435.9,439.5,444.3
XS GIS Cut Line= 3
     1853690.205      347020.059     1853140.972      346987.918
     1852663.729      346987.507
#Sta/Elev= 30
       0 1535.87     9.8  1535.3    29.5 1528.39    49.1 1529.46   137.5 1518.83
     167 1518.33   206.3  1513.1   216.1 1513.19   235.8 1516.75   255.4 1510.96
   265.3 1510.76   284.9 1514.68   343.9  1505.7   383.2 1502.32   451.9 1501.97
   510.9 1503.84   542.7 1498.06   550.2 1497.26   557.7 1497.53   570.1 1499.53
   589.9 1506.63   629.7 1530.78   649.6 1540.38   719.2 1566.65     749 1574.39
   818.6 1599.38   868.3 1612.18   947.9 1635.61   977.7    1640  1027.4  1643.3
#Mann= 3 , 0 , 0
       0      .1       0   542.7    .045       0   557.7      .1       0
Bank Sta=542.7,557.7
XS Rating Curve= 0 ,0
Exp/Cntr=0.3,0.1

Type RM Length L Ch R = 1 ,6356.8  ,502.1,486.9,470.1
XS GIS Cut Line= 4
     1853716.174      346777.582     1853467.476      346618.728
     1853205.324      346557.096     1852873.292        346622.2
#Sta/Elev= 30
       0 1516.27    19.7 1514.47    39.4 1513.78      59 1510.96    78.7 1509.82
   108.2 1505.87   216.4 1497.04   245.9 1493.72   295.1 1493.89     315 1492.02
     345 1491.42   374.9  1489.1   384.9 1488.92   414.8 1489.87   454.7 1487.73
   464.8 1486.62   474.6 1485.91   479.8 1486.18   504.6 1489.12   534.5 1490.76
   554.4  1492.5   564.4  1494.5   594.3 1503.51   614.2 1510.16   673.9 1524.22
   683.8  1525.9   753.5 1530.92   773.4  1532.8   833.1 1534.09   902.8 1541.47
#Mann= 3 , 0 , 0
       0      .1       0   464.8    .045       0   479.8     .08       0
#XS Ineff= 2 , 0
          414.22 1490.57
Permanent Ineff=
       F       F
Bank Sta=464.8,479.8
XS Rating Curve= 0 ,0
Exp/Cntr=0.3,0.1

Type RM Length L Ch R = 1 ,5869.8  ,131.2,145.7,145.9
XS GIS Cut Line= 4
     1853820.413      346036.986     1853540.465       346091.24
     1853349.493      346186.726     1852859.042      346555.649
#Sta/Elev= 30
       0 1574.51    29.5 1561.58      59 1550.15   108.2 1535.44   137.7 1523.33
   157.3  1517.1     177 1509.51   216.3 1498.13   275.3 1483.36   294.9  1479.5
   362.8 1477.28   379.7 1474.43   382.2 1474.04   394.7 1475.52   411.3  1477.1
     421 1476.59   440.4  1477.4   498.7  1475.4   577.9 1490.32   696.6  1502.8
   765.9 1508.25   864.9 1514.73   894.6 1514.85   934.2 1517.44   993.6 1517.78
  1033.2 1519.86    1053 1522.39  1082.7  1529.5  1092.6 1530.85  1112.4 1531.24
#Mann= 3 , 0 , 0
       0      .1       0   379.7    .045       0   394.7      .1       0
Bank Sta=379.7,394.7
XS Rating Curve= 0 ,0
Exp/Cntr=0.3,0.1

Type RM Length L Ch R = 1 ,5724.2  ,69.9,55.3,54.3
XS GIS Cut Line= 4
     1853643.764      345917.628     1853439.771      346032.646
     1853240.118      346138.983     1852682.392       346568.67
#Sta/Elev= 30
       0 1539.01    29.3 1529.57    58.6 1518.68   126.8 1499.46   156.1 1492.15
   175.6 1489.32   195.2 1485.08   214.7  1482.5   253.8 1474.85   283.4 1474.48
   312.9 1475.54   322.7    1475   332.5  1473.1   352.2 1472.55   363.2 1471.48
   381.7  1470.7  381.93 1470.73   391.5 1472.55   401.4  1475.6   411.2 1477.76
   470.3 1480.61   519.9 1485.16   589.3 1488.52     619 1491.57   678.6 1494.42
   807.5 1497.45   886.8 1500.19  1055.4 1509.26  1134.7 1516.59  1164.4 1520.24
#Mann= 3 , 0 , 0
       0     .08       0   363.2    .045       0  381.93     .07       0
Bank Sta=363.2,381.93
XS Rating Curve= 0 ,0
Exp/Cntr=0.3,0.1

Type RM Length L Ch R = 1 ,5668.8  ,211.1,211.8,212.7
XS GIS Cut Line= 4
     1853602.097      345880.302     1853398.104      345995.319
     1853198.451      346101.656     1852640.726      346531.344
#Sta/Elev= 30
       0 1536.19      39 1522.65   126.8  1497.2   185.4  1484.4   253.8  1473.9
   273.5 1473.21   332.5 1474.11   342.4 1473.28   358.5 1468.79     362 1467.83
   373.5    1470   381.7 1473.34   391.5 1475.02     421 1476.06   470.3 1476.22
     510  1473.4   609.1  1475.4   648.8 1474.54   688.5 1476.34   728.1 1475.77
     738 1477.48   767.8 1477.82   787.6 1481.17   807.5  1482.9   956.2 1489.12
  1015.7 1493.25  1114.9 1494.75  1144.6 1496.74  1154.5 1496.41  1164.4 1497.96
#Mann= 3 , 0 , 0
       0     .07       0   358.5    .045       0   373.5      .1       0
#XS Ineff= 2 , 0
          332.69 1474.11  431.44         1476.11
Permanent Ineff=
       F       F
Bank Sta=358.5,373.5
XS Rating Curve= 0 ,0
Exp/Cntr=0.3,0.1

Type RM Length L Ch R = 1 ,5457    ,441.8,457.3,472.6
XS GIS Cut Line= 4
     1853642.028      345777.437     1853255.743      345842.542
     1853058.897      345937.001     1852585.829      346164.008
#Sta/Elev= 30
       0 1562.25    68.6 1544.86    97.9 1536.94   107.7  1533.8   137.1 1526.62
   156.7 1519.34   166.5 1520.15   225.2 1505.85   254.6 1497.38     284 1486.65
   303.6 1481.33   313.4  1479.4     333 1476.62   362.4 1474.06   381.9 1471.76
   451.3  1469.2   485.9  1465.3     491 1465.03   500.9 1465.46   520.8 1468.52
   580.3 1470.39   629.9 1471.11   669.5 1473.71   689.3 1475.81   738.8 1491.03
   788.3 1504.17     917 1532.42   956.6 1539.52  1045.7 1553.17  1134.8  1564.8
#Mann= 3 , 0 , 0
       0     .08       0   485.9    .045       0   500.9     .08       0
Bank Sta=485.9,500.9
XS Rating Curve= 0 ,0
Exp/Cntr=0.3,0.1

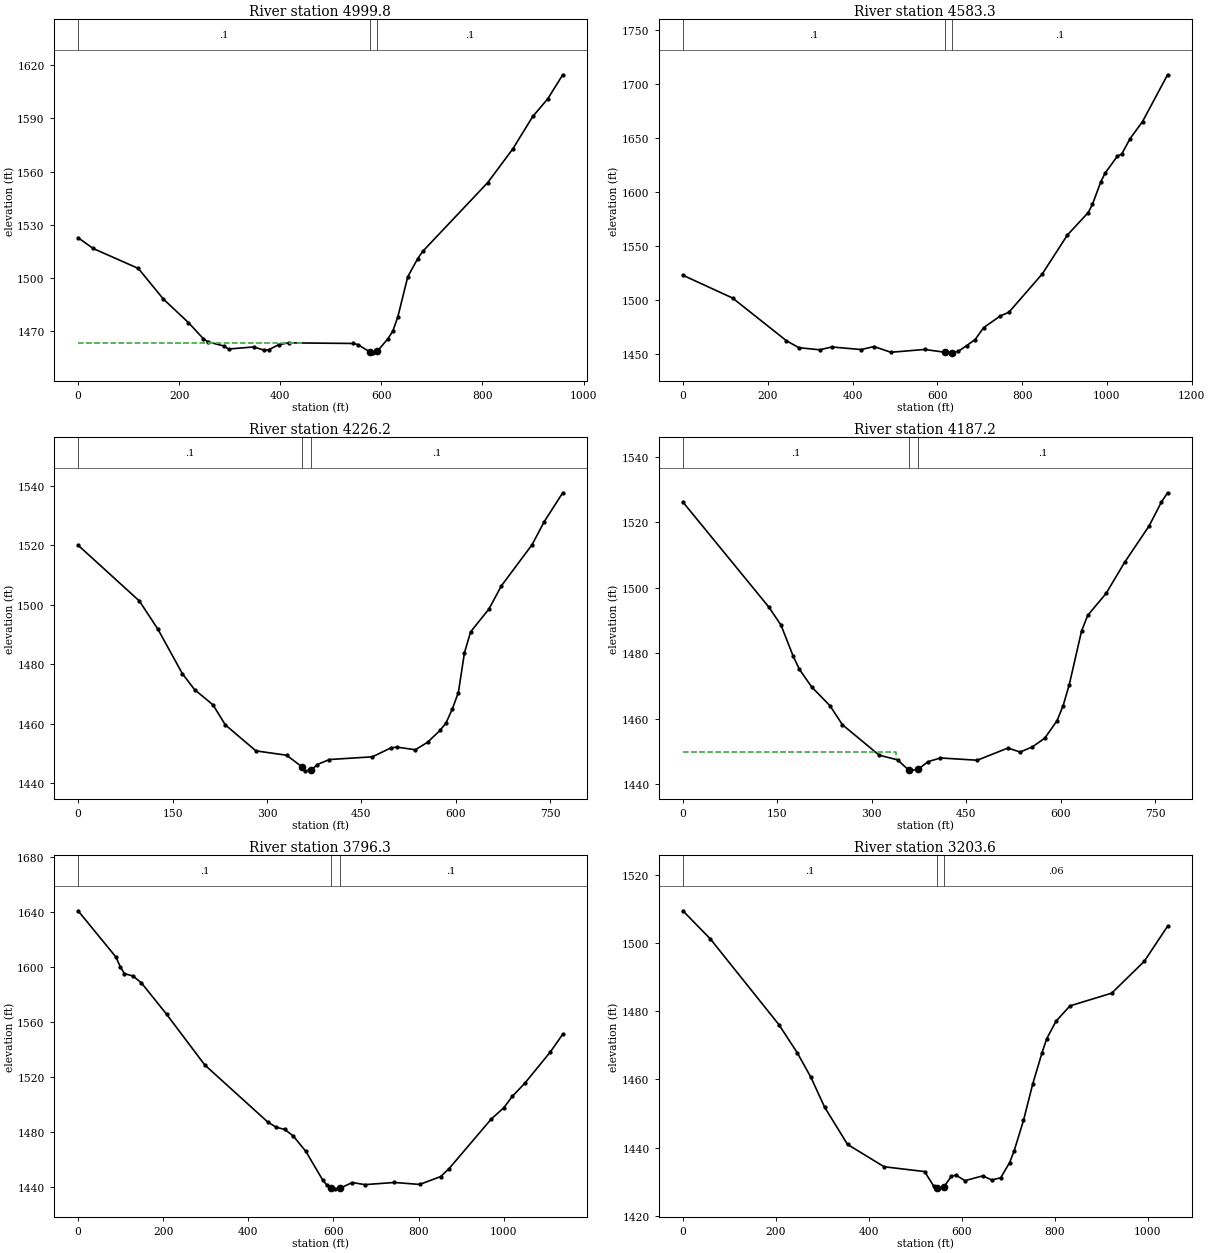
Type RM Length L Ch R = 1 ,4999.8  ,394.1,416.4,438.7
XS GIS Cut Line= 4
     1853484.476      345703.653     1853097.323      345549.139
     1852887.254      345500.528     1852560.865      345493.583
#Sta/Elev= 30
       0 1522.69    29.8 1516.61   119.1 1505.37   168.7 1488.11   218.4 1474.82
   248.1 1465.66     258 1463.87   287.8 1461.69   297.8 1459.93   347.4  1461.1
   367.2 1459.39   377.2  1459.5     397  1462.4   416.8 1463.41   544.3 1463.06
   554.1 1462.38   576.7 1458.34   583.5 1457.78   591.7 1458.61   612.9 1465.67
   622.7 1470.04   632.5 1477.96   652.2 1500.65     672 1510.92   681.9    1515
   810.5 1553.78     860 1572.72   899.6 1591.04   929.2 1600.99   958.9 1614.54
#Mann= 3 , 0 , 0
       0      .1       0   576.7    .045       0   591.7      .1       0
#XS Ineff= 2 , 0
          446.18 1463.48
Permanent Ineff=
       F       F
Bank Sta=576.7,591.7
XS Rating Curve= 0 ,0
Exp/Cntr=0.3,0.1

Type RM Length L Ch R = 1 ,4583.3  ,343.6,357.1,370.3
XS GIS Cut Line= 4
     1853498.365      345686.292     1853248.365      345411.986
     1853106.004      345030.042     1852934.129      344708.861
#Sta/Elev= 30
       0 1523.08   117.2 1501.97   244.2 1462.48   273.5 1456.05   322.3  1454.1
   351.6 1456.69   420.8 1454.31   450.7 1457.11   490.4 1451.81     570  1454.4
   619.2 1451.77   629.6 1451.28   634.2 1451.35   649.5 1452.64   669.4 1457.99
   689.3 1463.62   709.2 1474.61   748.9 1485.45   768.8 1488.81   847.7 1524.36
   906.7 1560.24     956 1581.09   965.8  1588.6   985.5 1609.39   995.4 1617.33
  1024.9 1633.38  1034.7 1635.06  1054.4  1649.3    1084 1665.26    1143 1708.52
#Mann= 3 , 0 , 0
       0      .1       0   619.2    .045       0   634.2      .1       0
#XS Ineff= 2 , 0
          450.91 1456.94
Permanent Ineff=
       F       F
Bank Sta=619.2,634.2
XS Rating Curve= 0 ,0
Exp/Cntr=0.3,0.1

Type RM Length L Ch R = 1 ,4226.2  ,39.1,39,39
XS GIS Cut Line= 4
      1853513.99      345651.569     1853442.809      345408.514
     1853498.365      345151.569     1853467.115      344899.833
#Sta/Elev= 30
       0 1520.09    97.4  1501.3   126.6 1491.89   165.6 1476.87   185.1 1471.48
   214.3 1466.36   233.8 1459.64   282.5 1450.87   331.2 1449.42     355 1445.59
   360.4 1444.16   370.5 1444.36   379.8 1446.29   399.3 1447.97   467.5 1448.88
   496.7 1451.88   506.4 1452.15   535.7 1451.25   555.2 1453.79   574.7 1457.74
   584.4 1460.28   594.2 1464.87     604 1470.52   613.7 1483.93   623.5 1490.94
   652.7 1498.66   672.2 1506.38     721 1520.24   740.5 1528.06   769.8 1537.73
#Mann= 3 , 0 , 0
       0      .1       0     355    .045       0   370.5      .1       0
Bank Sta=355,370.5
XS Rating Curve= 0 ,0
Exp/Cntr=0.3,0.1

Type RM Length L Ch R = 1 ,4187.2  ,413.4,390.9,369.8
XS GIS Cut Line= 4
     1853552.184      345656.778     1853481.004      345413.722
     1853536.559      345156.778     1853505.309      344905.042
#Sta/Elev= 30
       0 1526.12   136.4 1494.08   155.8 1488.56   175.3 1479.01   185.1 1475.05
   204.6 1469.67   233.8  1463.9   253.3 1458.16   311.7 1448.86   340.9 1447.42
   358.7  1444.3   360.4 1444.07   373.7 1444.58   389.6 1446.88     409    1448
   467.5 1447.31   516.2 1451.03   535.7 1449.81   555.2  1451.4   574.7 1454.03
   594.2 1459.34     604    1464   613.7  1470.4   633.2 1486.75     643 1491.53
   672.2 1498.23   701.5 1507.68   740.5 1518.83   760.1 1526.13   769.8 1528.94
#Mann= 3 , 0 , 0
       0      .1       0   358.7    .045       0   373.7      .1       0
#XS Ineff= 2 , 0
          338.26  1449.8
Permanent Ineff=
       F       F
Bank Sta=358.7,373.7
XS Rating Curve= 0 ,0
Exp/Cntr=0.3,0.1

Type RM Length L Ch R = 1 ,3796.3  ,604.2,592.7,578.1
XS GIS Cut Line= 3
     1854289.864      345654.794     1853862.263      345227.289
     1853508.781      344826.917
#Sta/Elev= 30
       0 1640.95    89.2 1607.13    99.1 1600.17     109 1595.18   128.9 1593.43
   148.7 1588.46   208.2 1565.46   297.4 1528.71     446 1486.95   465.9 1483.22
   485.7 1481.63   505.5 1476.87   535.3  1465.6   574.9 1444.68   584.8    1441
   594.7 1438.88   604.6 1438.38   614.5 1438.72   644.2 1442.97   673.9 1441.45
   743.1 1443.02   802.5 1441.59   851.9 1447.33   871.7 1453.15   970.6 1489.19
  1000.3  1497.5    1020 1505.68  1049.7 1515.38  1109.1 1537.93  1138.7 1551.05
#Mann= 3 , 0 , 0
       0      .1       0   594.7    .045       0   614.5      .1       0
Bank Sta=594.7,614.5
XS Rating Curve= 0 ,0
Exp/Cntr=0.3,0.1

Type RM Length L Ch R = 1 ,3203.6  ,515.1,493.5,471.8
XS GIS Cut Line= 4
     1854727.531      344853.826     1854282.653      344771.361
     1854030.917      344706.257     1853701.056      344699.746
#Sta/Elev= 30
       0 1509.55      59 1501.29   206.6 1476.08   245.9 1467.86   275.4 1460.61
   304.9 1451.83   354.1 1440.91   432.8 1434.35   519.9 1432.93   539.1 1428.72
     546 1428.11   548.8 1427.86     561 1428.36   577.6 1431.57   587.3 1431.89
   606.5 1430.26   645.1 1431.67   664.3 1430.46   683.6 1431.12   702.8 1435.59
   712.5 1439.04   732.5 1447.94   752.5  1458.7   772.5 1467.88   782.5 1471.95
   802.5 1477.11   832.4  1481.6   922.4 1485.36   992.4 1494.72  1042.4 1505.01
#Mann= 3 , 0 , 0
       0      .1       0     546    .045       0     561     .06       0
Bank Sta=546,561
XS Rating Curve= 0 ,0
Exp/Cntr=0.3,0.1

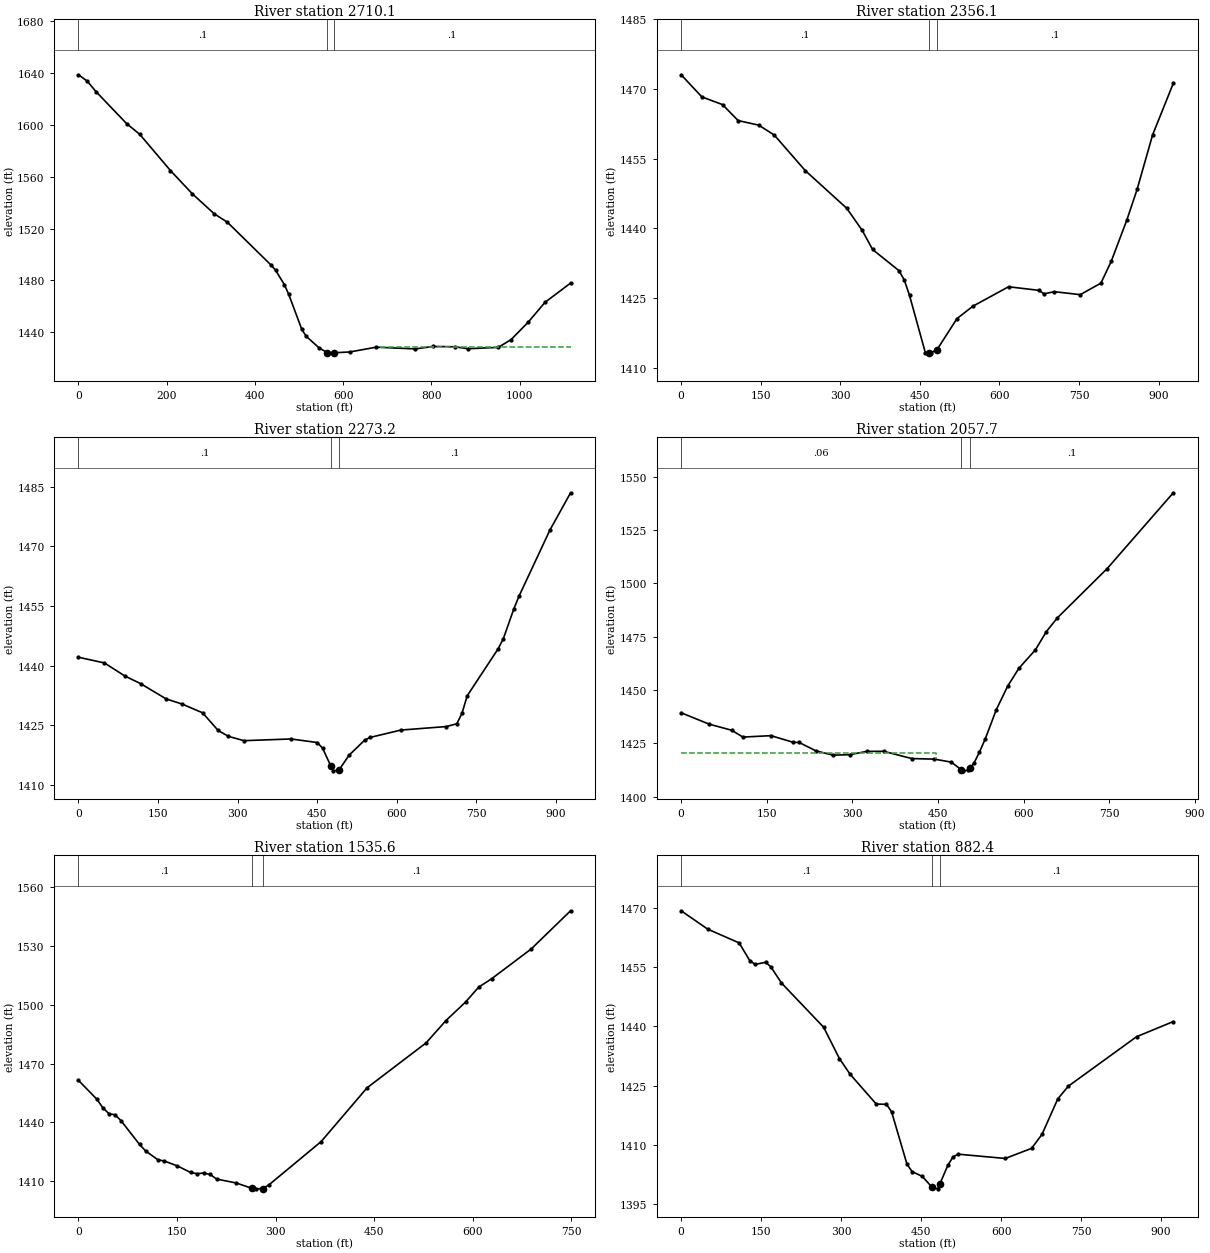
Type RM Length L Ch R = 1 ,2710.1  ,389.2,354,318.7
XS GIS Cut Line= 4
     1854738.382      343961.899     1854373.799      344202.785
     1853990.552      344531.778     1853871.195      344657.646
#Sta/Elev= 30
       0 1638.83    19.9 1633.93    39.7 1625.84   109.2 1601.11     139  1592.8
   208.6 1564.83   258.2 1546.86   307.9 1531.42   337.7  1524.9     437 1491.71
   446.9  1487.8   466.7 1476.77   476.6 1469.24   506.3 1442.14   516.2 1436.83
   545.9 1427.76   563.7 1424.31   565.7 1424.06   578.7  1424.1   615.2 1424.74
   674.7 1428.43   763.8 1427.09   803.4 1428.98   852.9 1428.76   882.6 1427.23
   951.7 1428.29   980.6 1434.27  1019.2 1447.66  1057.7 1463.12  1115.5 1477.94
#Mann= 3 , 0 , 0
       0      .1       0   563.7    .045       0   578.7      .1       0
#XS Ineff= 2 , 0
                           683.9         1428.45
Permanent Ineff=
       F       F
Bank Sta=563.7,578.7
XS Rating Curve= 0 ,0
Exp/Cntr=0.3,0.1

Type RM Length L Ch R = 1 ,2356.1  ,81.7,82.9,84.3
XS GIS Cut Line= 5
     1853845.153       343783.08     1853864.684      344143.323
     1853984.042      344314.764     1854010.083       344405.91
     1853858.174      344620.753
#Sta/Elev= 30
       0 1473.08      39 1468.32      78 1466.66   107.3 1463.23   146.3 1462.24
   175.5 1460.11     234 1452.45     312 1444.36   341.3 1439.59   360.8 1435.48
   410.5 1430.93   420.5 1428.92   430.4 1425.61   460.2 1413.28   467.1 1413.25
   470.2 1413.24   482.1  1413.9   519.9 1420.61   549.8 1423.27   617.1 1427.46
   674.2 1426.69     684 1425.94   703.4  1426.4   752.2 1425.76   791.2 1428.24
   810.6 1432.92   839.9 1441.78   859.4 1448.41   888.6 1460.14   927.6 1471.23
#Mann= 3 , 0 , 0
       0      .1       0   467.1    .045       0   482.1      .1       0
Bank Sta=467.1,482.1
XS Rating Curve= 0 ,0
Exp/Cntr=0.3,0.1

Type RM Length L Ch R = 1 ,2273.2  ,193.2,215.6,237.5
XS GIS Cut Line= 5
     1853758.347       343787.42     1853777.879      344147.663
     1853897.236      344319.104     1853923.278       344410.25
     1853771.368      344625.094
#Sta/Elev= 30
       0 1442.09    48.8 1440.66    87.8 1437.34     117 1435.45   165.8 1431.56
     195 1430.32     234 1428.09   263.3 1423.64   282.8 1422.15     312 1421.07
   400.6  1421.5   450.3  1420.6   460.2 1419.15     476  1414.6   480.1 1413.47
     491 1413.66     510  1417.4   539.8 1421.24   549.8 1421.89   607.6 1423.74
   693.7 1424.63   713.2 1425.34   722.9 1427.96   732.7 1432.37   791.2 1444.25
   800.9 1446.78   820.4 1454.18   830.1  1457.4   888.6 1474.12   927.6 1483.53
#Mann= 3 , 0 , 0
       0      .1       0     476    .045       0     491      .1       0
Bank Sta=476,491
XS Rating Curve= 0 ,0
Exp/Cntr=0.3,0.1

Type RM Length L Ch R = 1 ,2057.7  ,499.4,522.1,543.7
XS GIS Cut Line= 4
     1853743.156       343791.76     1853730.135      344017.455
     1853608.608      344351.656     1853510.951      344614.243
#Sta/Elev= 30
       0 1439.26    49.2 1433.92    88.5 1431.07   108.1 1427.87   157.3 1428.54
   196.6 1425.38   206.4 1425.37     236 1421.41   265.6 1419.41   295.2 1419.61
   324.8 1421.15   354.5 1421.21   403.9 1417.79   443.4 1417.53     473 1416.13
   490.7 1412.52   492.8 1412.04   502.7  1412.4   505.7 1413.36   512.5 1415.52
   522.4 1420.86   532.3 1426.88     552  1440.8   571.8 1451.76   591.3 1460.09
   620.3 1468.75   639.6 1477.37     659 1483.84   745.9 1506.86   861.8 1542.44
#Mann= 3 , 0 , 0
       0     .06       0   490.7    .045       0   505.7      .1       0
#XS Ineff= 2 , 0
          446.05 1420.59
Permanent Ineff=
       F       F
Bank Sta=490.7,505.7
XS Rating Curve= 0 ,0
Exp/Cntr=0.3,0.1

Type RM Length L Ch R = 1 ,1535.6  ,660.6,653.2,646
XS GIS Cut Line= 4
     1853788.729      343707.125     1853673.712      343744.017
     1853413.295      343809.121     1853107.306      343997.924
#Sta/Elev= 30
       0 1461.48    27.9  1451.9    37.2 1447.47    46.5 1444.47    55.8 1443.92
      65 1440.84    92.9 1428.82   102.2 1425.48   120.8    1421   130.7 1420.35
   150.6 1417.85   170.5 1414.55   180.4 1413.88   190.4 1414.23   200.3 1413.52
   210.3 1411.15   240.1 1409.15   263.9 1406.44   269.9 1406.17  280.22 1406.26
   289.8 1408.19   369.3 1430.28   439.2 1457.71     529 1480.61     559 1491.92
     589 1501.42     609 1509.03   628.9 1513.35   688.8 1528.47   748.8 1547.96
#Mann= 3 , 0 , 0
       0      .1       0   263.9    .045       0  280.22      .1       0
Bank Sta=263.9,280.22
XS Rating Curve= 0 ,0
Exp/Cntr=0.3,0.1

Type RM Length L Ch R = 1 ,882.4   ,383.8,385.1,384.3
XS GIS Cut Line= 4
     1853762.688       343010.51     1853426.316      343127.698
     1853280.917      343221.014     1852972.757       343466.24
#Sta/Elev= 30
       0 1469.36    49.5 1464.72   108.8  1461.2   128.6 1456.71   138.5 1455.75
   158.3 1456.28   168.2 1455.13     188 1451.04   267.2 1439.79   296.8 1431.84
   316.6  1427.9   365.8  1420.3     385 1420.23   394.6 1418.33   423.4 1405.06
     433 1403.16   452.2 1401.93   470.1 1399.23     481 1398.78   485.1 1400.03
   500.2 1404.79   509.8 1406.89   519.4 1407.58   607.7 1406.49     657 1409.05
   676.6  1412.6   706.2 1421.61   725.9 1424.83   853.9 1437.39   922.8 1441.24
#Mann= 3 , 0 , 0
       0      .1       0   470.1    .045       0   485.1      .1       0
Bank Sta=470.1,485.1
XS Rating Curve= 0 ,0
Exp/Cntr=0.3,0.1

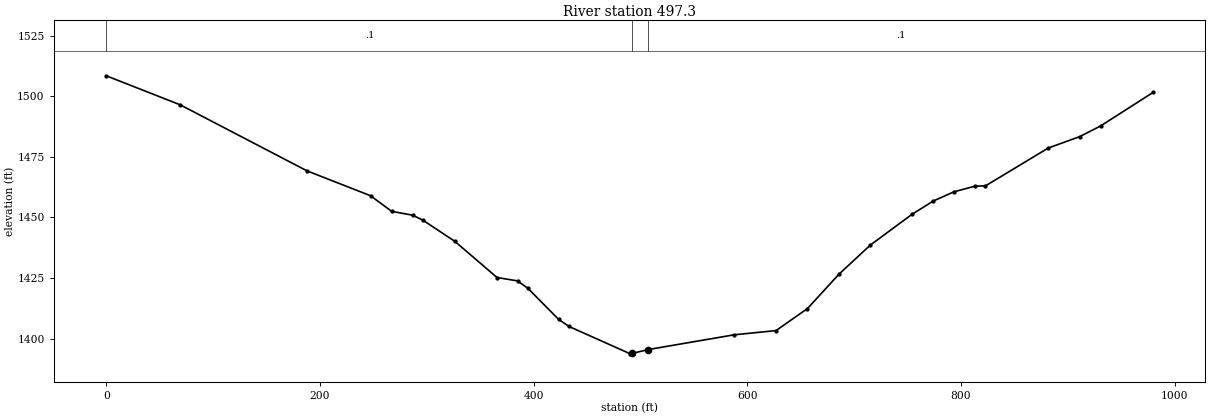
Type RM Length L Ch R = 1 ,497.3   ,485.1,497.3,510.2
XS GIS Cut Line= 4
     1853576.056        342691.5     1853239.684      342808.687
     1853094.285      342902.003      1852714.51      343145.059
#Sta/Elev= 30
       0 1508.52    69.3 1496.52     188 1469.24   247.4 1458.98   267.2 1452.53
   286.9 1450.93   296.8 1448.77   326.5 1440.08   365.8 1425.19     385  1423.8
   394.6 1420.78   423.4 1407.94     433 1405.01   490.6 1393.67   492.6 1393.88
   507.6 1395.46   587.8 1401.53     627 1403.28   656.4 1412.37   685.8 1426.53
   715.2 1438.57   754.4 1451.34     774 1456.75   793.6 1460.61   813.2 1462.92
     823 1463.04   881.8 1478.68   911.2 1483.38   930.8 1487.79   979.9 1501.65
#Mann= 3 , 0 , 0
       0      .1       0   492.6    .045       0   507.6      .1       0
Bank Sta=492.6,507.6
XS Rating Curve= 0 ,0
Exp/Cntr=0.3,0.1

Chan Stop Cuts=-1
Use User Specified Reach Order=0
Composite Channel Slope=5